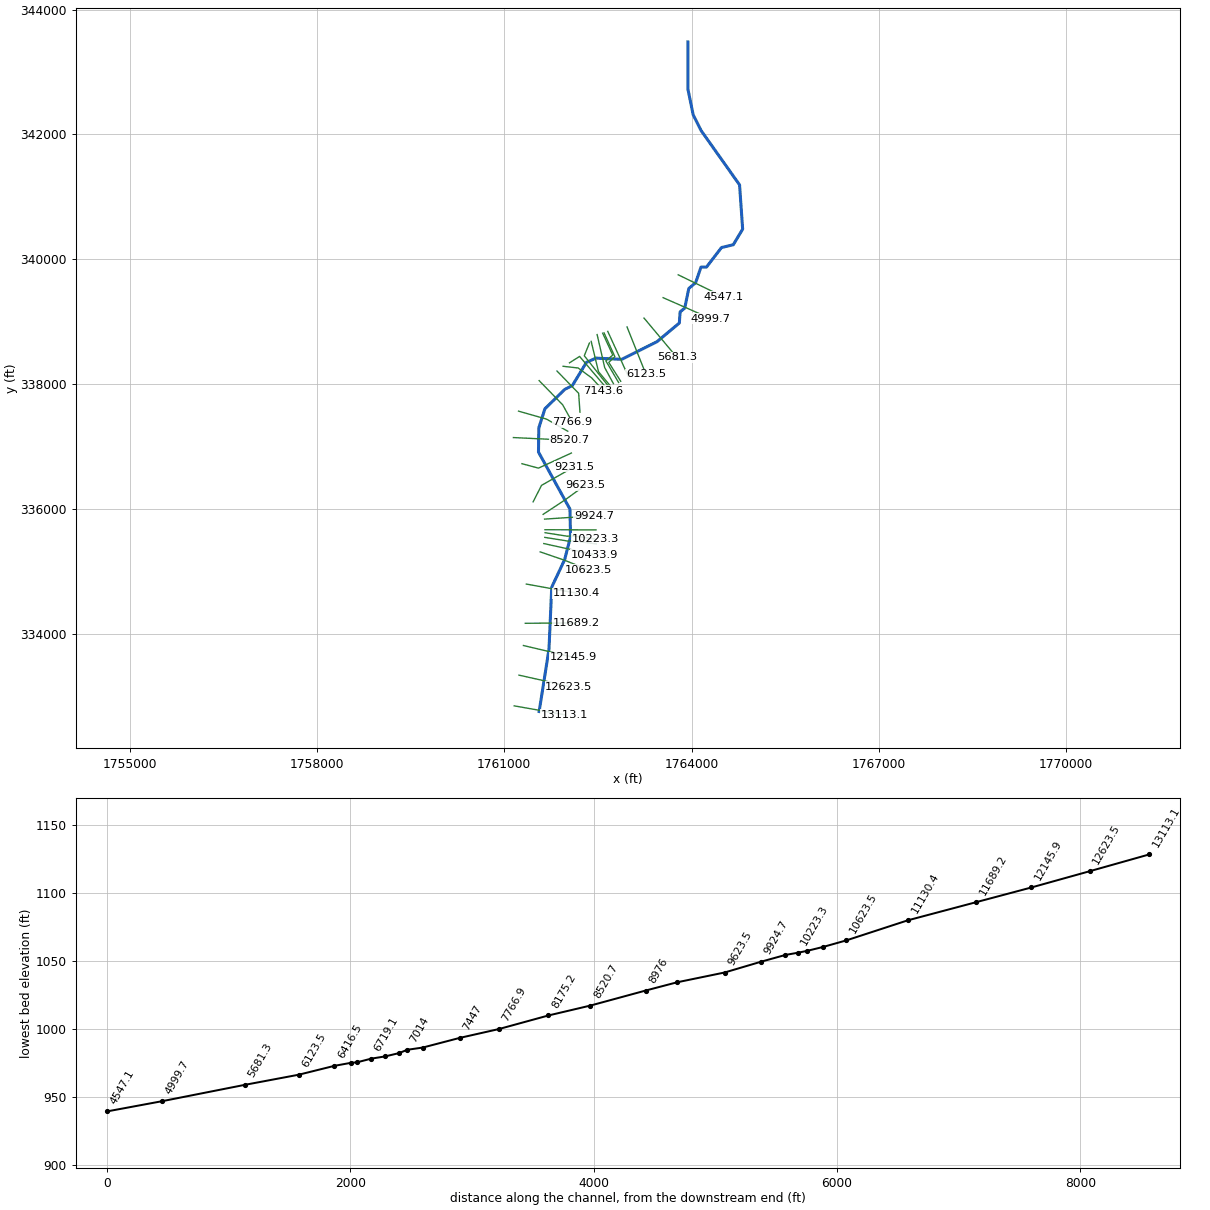
--- CASEYCK.prj (project) ---

Proj Title=CASEYCK
Current Plan=p01
Default Exp/Contr=0,0
English Units
Geom File=g01
Flow File=f01
Plan File=p01
BEGIN DESCRIPTION:
END DESCRIPTION:
DSS Export Rating Curves= 0
DSS Export Rating Curve Sorted= 0
DSS Export Volume Flow Curves= 0
DXF OffsetX= 0
DXF OffsetY= 0
DXF ScaleX= 0
DXF ScaleY= 0

--- CASEYCK.p01 (plan) ---

Plan Title=Floodplain
Program Version=4.00
Geom File=g01
Flow File=f01
K Sum by GR=0
Std Step Tol=0.01
Critical Tol=0.01
Num of Std Step Trials=20
Max Error Tol=0.3
Flow Tol Ratio=0.001
Split Flow NTrial=30
Split Flow Tol=0.02
Split Flow Ratio=0.02
Log Output Level=0
Friction Slope Method=1
Unsteady Friction Slope Method=2
Unsteady Bridges Friction Slope Method=1
Global Log Level=0
CheckData=False
Run HTab=0
Run UNet=0
Run PostProcess=0
UNET Theta=0
UNET Theta Warmup=0
UNET ZTol=0
UNET ZSATol=0
UNET MxIter=0
UNET MaxInSteps=0
UNET DtIC=0
UNET DtMin=0
UNET MaxCRTS=0
UNET WFStab=0
UNET SFStab=0
UNET WFX=0
UNET SFX=0
UNET DSS MLevel=0
UNET DZMax Abort=0
UNET Convert EG Bridges=0
UNET Use Existing IB Tables=0
UNET Froude Limit=0
UNET Froude Power=0
Write IC File=0
Echo Input=False
Echo Output=False
Write Detailed=0

--- CASEYCK.f01 (steady flow) ---

Flow Title=NFF Regression Equation
Program Version=4.00
Number of Profiles=1
Profile Names=P100yr
River Rch & RM=CASEYCK,Main      ,13113.1
974.2092
River Rch & RM=CASEYCK,Main      ,10623.5
1068.230
River Rch & RM=CASEYCK,Main      ,7447
1144.757
River Rch & RM=CASEYCK,Main      ,6719.1
1426.762
River Rch & RM=CASEYCK,Main      ,5681.3
1435.975
River Rch & RM=CASEYCK,Main      ,465.2
1593.371
River Rch & RM=CASEYCK,Main      ,128.8
1598.308
Boundary for River Rch & Prof#=CASEYCK,Main      ,1
Up Type=0
Dn Type=3
Dn Slope=0.014807

--- CASEYCK.g01 (geometry) ---

Geom Title=USGS 10m DEM
Program Version=5.03

River Reach=CASEYCK         ,Main
Reach XY= 30
     1761558.367      332757.529     1761715.762      333754.259
     1761759.887      334750.488     1761966.866      335190.329
     1762060.575       335555.34     1762051.932       335999.14
     1761547.787      336912.958     1761552.995      337301.153
     1761651.086      337607.229     1761969.662      337917.993
     1762090.322      337978.062     1762315.148      338349.417
     1762468.794      338417.993     1762879.384      338398.028
     1763447.961      338682.576     1763803.863      338980.319
     1763816.016      339157.402     1763889.801      339219.034
     1763955.773      339534.312      1764064.28       339624.59
     1764150.218      339874.764     1764237.891      339875.632
      1764479.21      340189.173     1764667.579      340233.444
     1764817.752      340483.444     1764768.273      341192.732
     1764154.558      342059.052     1764025.217       342314.26
     1763941.884      342723.288     1763940.148      343481.361

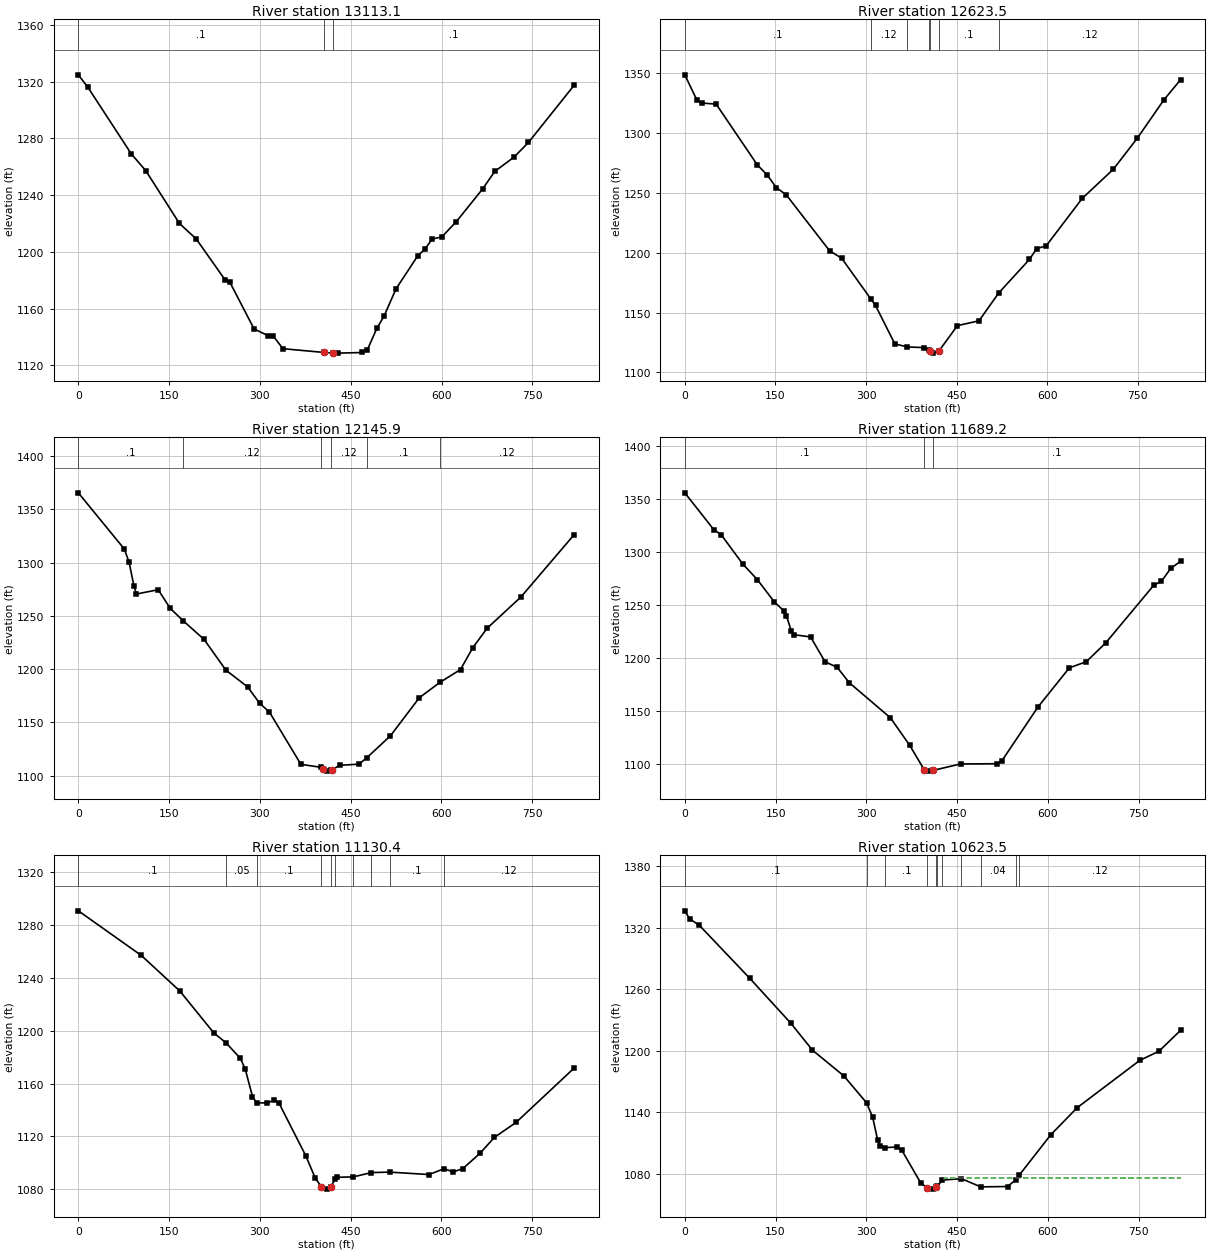
Type RM Length L Ch R = 1 ,13113.1 ,490.4,489.6,488.2
XS GIS Cut Line= 3
     1761158.543      332848.473     1761561.816      332777.332
     1761965.089       332706.19
#Sta/Elev= 30
       0 1324.86    15.9    1316    87.5 1269.07   111.3  1257.3     167 1220.01
   194.8 1209.04   242.5 1180.15   250.5 1178.39   290.2 1145.65   314.1 1140.66
     322 1140.58   337.9 1131.65   405.7    1129   420.7 1128.57   429.4 1128.52
   469.1 1128.97   477.1 1130.54     493 1145.93   504.9 1154.56   524.8  1173.9
   560.6 1197.13   572.5 1201.87   584.4 1209.04   600.3 1210.48   624.2 1221.21
   667.9 1244.41   687.8  1256.7   719.6 1266.78   743.5 1277.15     819 1317.52
#Mann= 3 , 0 , 0
       0      .1       0   405.7    .045       0   420.7      .1       0
Bank Sta=405.7,420.7
XS Rating Curve= 0 ,0
Exp/Cntr=0.3,0.1

Type RM Length L Ch R = 1 ,12623.5 ,477.6,477.6,477.3
XS GIS Cut Line= 3
     1761234.193      333340.632     1761635.883      333251.046
     1762034.414      333158.122
#Sta/Elev= 30
       0 1348.55      20  1327.5      28 1324.99    51.9  1324.1   119.9 1273.45
   135.8 1265.24   151.8 1254.25   167.8 1248.43   239.7 1201.62   259.7 1195.37
  307.651161.617   315.7 1155.95   347.6 1123.97  368.18 1121.29   395.6 1120.81
   404.1  1118.5  405.841117.749   411.6 1116.16  421.111118.244   451.3  1139.1
     487 1143.15  519.721166.436   570.5 1194.39   582.4 1203.37   598.3  1205.8
   657.9 1245.35   709.5 1269.77   749.3 1295.77     793 1327.57   820.8 1344.53
#Mann= 7 ,-1 , 0
       0      .1       0  307.65     .12       0  368.18      .1       0
   404.1    .045       0  405.84    .045       0  421.11      .1       0
  519.72     .12       0
Bank Sta=405.84,421.11
XS Rating Curve= 0 ,0
Exp/Cntr=0.3,0.1

Type RM Length L Ch R = 1 ,12145.9 ,451.3,456.8,462
XS GIS Cut Line= 2
     1761306.712      333814.734     1762104.674      333627.268
#Sta/Elev= 30
       0 1365.54      76 1312.77      84 1300.17      92  1277.9      96  1270.5
     132 1274.58   151.9 1257.08   173.31245.416   207.9 1227.88   243.9 1199.08
   279.9 1183.29   299.9 1167.82   315.9  1159.7   367.9 1110.63     402 1107.72
   403.8 1106.68   411.8 1104.23     417 1104.89   419.8 1105.49   431.8 1109.66
   463.8 1110.77   476.71116.684   515.8 1137.27   563.8  1173.2  598.061187.656
   631.8 1199.64   651.8 1219.82   675.7 1238.32   731.7 1267.74   819.7 1326.27
#Mann= 6 ,-1 , 0
       0      .1       0   173.3     .12       0     402    .045       0
     417     .12       0   476.7      .1       0  598.06     .12       0
Bank Sta=403.8,419.8
XS Rating Curve= 0 ,0
Exp/Cntr=0.3,0.1

Type RM Length L Ch R = 1 ,11689.2 ,562.9,558.8,554.6
XS GIS Cut Line= 2
     1761336.092      334170.646     1762155.098      334177.145
#Sta/Elev= 30
       0 1356.21    47.9 1321.43    59.9  1316.8    95.9 1288.89   119.9 1274.17
   147.8 1253.23   163.8 1244.62   167.8 1240.17   175.8 1226.04   179.8 1222.26
   207.8 1220.04   231.7 1196.61   251.7 1191.39   271.7 1176.83   339.6 1143.73
   371.6 1117.64   395.8  1094.3   403.5 1093.33   410.8 1094.13   455.5  1100.1
   515.4  1100.3   523.4 1102.79   583.3 1153.86   635.2 1190.89   663.2  1196.7
   695.2 1214.41   775.1  1269.2   787.1 1272.49     803 1285.03     819 1291.53
#Mann= 3 , 0 , 0
       0      .1       0   395.8    .045       0   410.8      .1       0
Bank Sta=395.8,410.8
XS Rating Curve= 0 ,0
Exp/Cntr=0.3,0.1

Type RM Length L Ch R = 1 ,11130.4 ,509.8,506.9,501.9
XS GIS Cut Line= 2
     1761353.081      334799.171     1762159.665      334653.133
#Sta/Elev= 30
       0 1290.82     104 1257.06   167.9 1230.06   223.9 1198.39  244.441190.718
   267.9 1179.05   275.9 1171.01   287.9 1150.17  294.561145.412   311.9 1145.33
   323.9 1147.33   331.9 1145.02   375.9 1105.42   391.9 1088.21   401.9 1081.85
   411.8 1080.04   416.9 1081.76  424.531087.422   427.8    1089  454.551089.314
  484.571092.569  514.581092.922   579.8 1091.09  604.631095.496   619.8 1093.04
   635.8 1095.64   663.8 1107.06   687.8  1119.2   723.7 1130.57   819.7 1171.73
#Mann= 10 ,-1 , 0
       0      .1       0  244.44     .05       0  294.56      .1       0
   401.9    .045       0   416.9      .1       0  424.53    .016       0
  454.55      .1       0  484.57     .06       0  514.58      .1       0
  604.63     .12       0
Bank Sta=401.9,416.9
XS Rating Curve= 0 ,0
Exp/Cntr=0.3,0.1

Type RM Length L Ch R = 1 ,10623.5 ,187,189.6,193.3
XS GIS Cut Line= 3
     1761575.325       335314.39     1761963.319      335181.463
     1762343.427      335029.419
#Sta/Elev= 30
       0 1336.54       8  1328.7    23.9 1322.48   107.5 1270.69   175.2 1226.99
     211 1200.69   262.8 1175.66  300.341149.432   310.6 1135.19   318.6 1113.31
   322.5 1107.33  331.561105.736   350.4 1106.23   358.4 1103.42   390.2 1071.01
  400.491066.579   410.1 1065.22  415.831066.997   417.6 1068.18  425.511074.056
  457.321075.392  489.131067.431   533.4 1067.76  546.981074.225  552.751078.852
   604.9  1118.2   648.6 1144.65     752 1190.74   783.8 1199.72   819.5 1220.07
#Mann= 11 ,-1 , 0
       0      .1       0  300.34     .05       0  331.56      .1       0
  400.49    .045       0  415.83    .045       0   417.6      .1       0
  425.51    .016       0  457.32      .1       0  489.13     .04       0
  546.98      .1       0  552.75     .12       0
#XS Ineff= 2 , 0
                          428.28         1076.35
Permanent Ineff=
       F       F
Bank Sta=400.49,415.83
XS Rating Curve= 0 ,0
Exp/Cntr=0.3,0.1

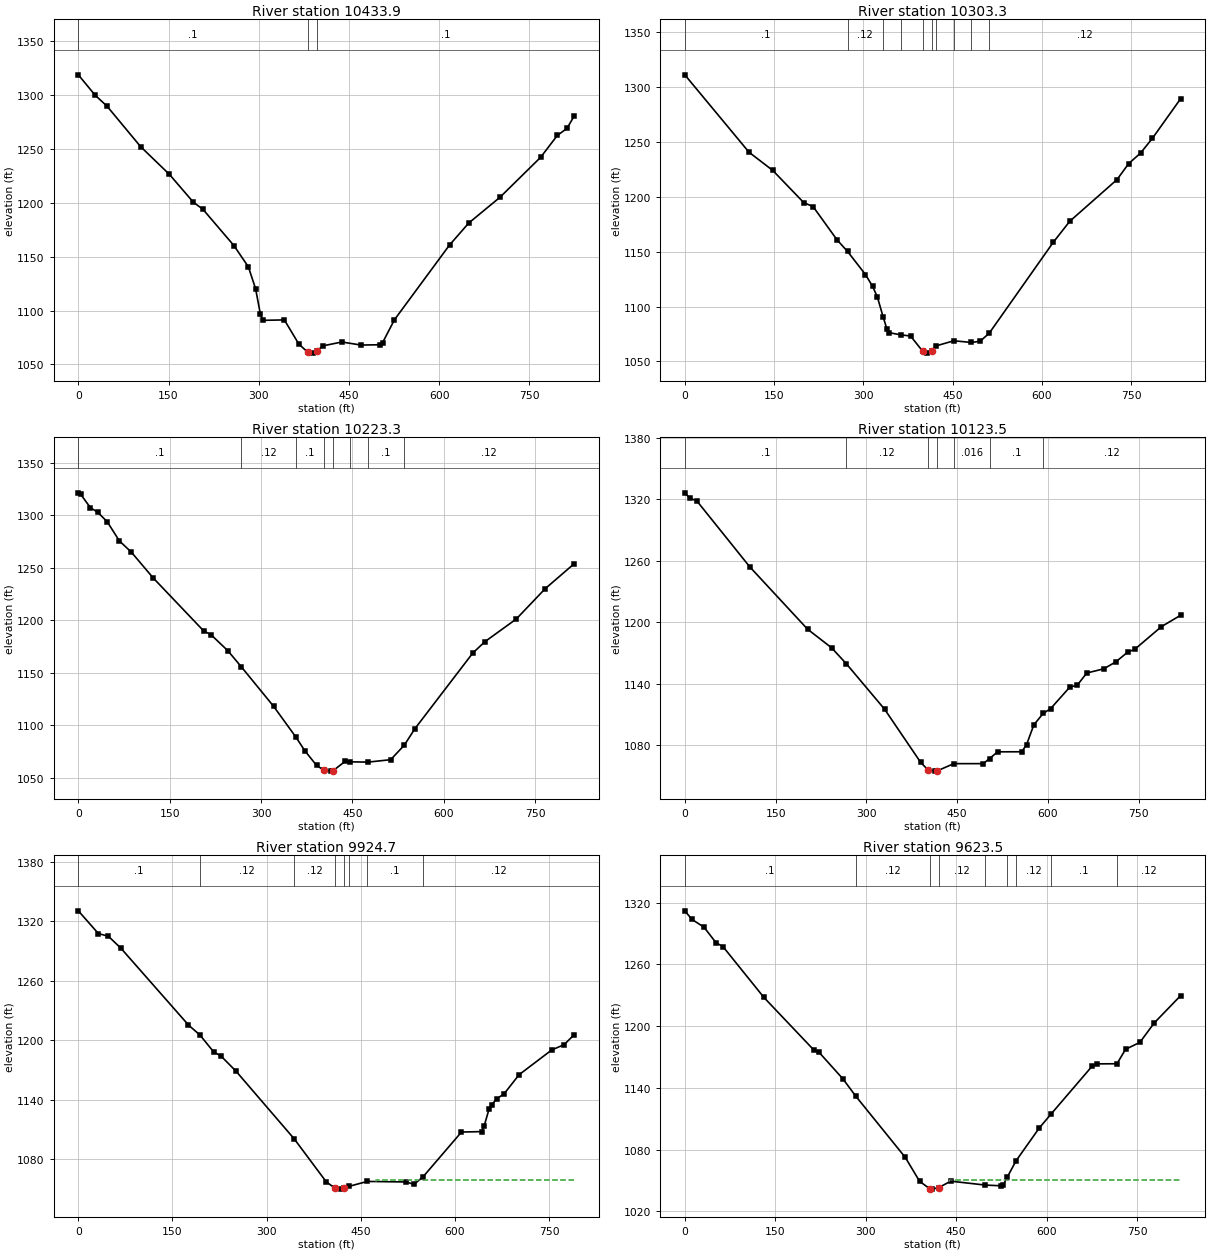
Type RM Length L Ch R = 1 ,10433.9 ,124.5,130.6,136.7
XS GIS Cut Line= 2
     1761633.086        335447.8     1762438.208      335270.934
#Sta/Elev= 30
       0 1318.78    27.9 1299.89    47.8 1289.62   103.5 1252.15   151.3 1226.42
   191.2 1200.53   207.1 1193.97   258.8 1160.17   282.7 1140.51   294.7 1120.17
   302.6 1096.86   306.6 1090.86   342.5 1091.28   366.4 1069.01   381.3 1061.24
   390.3 1060.43   396.3 1062.18   406.2 1067.12     438 1070.77   469.9 1067.93
   501.8 1068.21   505.7 1070.03   525.6 1091.47   617.2 1160.86   649.1 1181.21
   700.9 1205.08   768.6 1242.22   796.4 1262.58   812.4 1269.04   824.3 1280.54
#Mann= 3 , 0 , 0
       0      .1       0   381.3    .045       0   396.3      .1       0
Bank Sta=381.3,396.3
XS Rating Curve= 0 ,0
Exp/Cntr=0.3,0.1

Type RM Length L Ch R = 1 ,10303.3 ,80.2,80,79.8
XS GIS Cut Line= 4
     1761648.494      335546.975     1762019.327      335487.687
      1762108.39      335491.854     1762473.494      335441.854
#Sta/Elev= 30
       0 1311.31   107.9 1240.75   147.8 1224.14   199.8 1194.85   215.7 1191.09
   255.7 1160.92  273.471150.275   303.6 1129.22   315.6 1118.38   323.6 1108.72
   333.31090.594   339.6 1079.54   343.6 1076.18  363.21 1074.21   379.4 1073.13
   399.7 1059.29   406.6 1057.55   414.7  1059.4  422.491064.182  452.051068.807
  481.761067.274   496.4 1068.41  511.571075.722   619.2 1158.63     647 1177.82
   726.2 1215.73     746 1230.42   765.8 1239.93   785.7 1253.36   833.2 1289.52
#Mann= 10 ,-1 , 0
       0      .1       0  273.47     .12       0   333.3     .05       0
  363.21      .1       0   399.7    .045       0   414.7      .1       0
  422.49    .016       0  452.05      .1       0  481.76     .04       0
  511.57     .12       0
Bank Sta=399.7,414.7
XS Rating Curve= 0 ,0
Exp/Cntr=0.3,0.1

Type RM Length L Ch R = 1 ,10223.3 ,100.9,99.8,98.7
XS GIS Cut Line= 4
     1761654.484      335621.541     1762006.307      335565.812
     1762095.369      335569.979     1762460.473      335519.979
#Sta/Elev= 30
       0 1321.38       4 1319.86    19.8 1307.23    31.7 1302.91    47.5 1293.77
    67.3 1275.61    87.1 1264.78   122.7 1240.38   205.8 1189.71   217.7 1186.19
   245.4  1170.9  267.351155.671   320.6 1117.84  357.051088.607   371.7 1075.61
   391.1 1061.53   403.1    1057   414.4 1056.11   418.1 1056.45   437.6  1065.3
  445.761064.987  475.571064.701   512.7 1067.01   535.21080.946   552.4 1096.49
   647.5 1168.68   667.3 1179.46   718.8 1201.06   766.3 1229.97   813.9 1253.78
#Mann= 8 ,-1 , 0
       0      .1       0  267.35     .12       0  357.05      .1       0
   403.1    .045       0   418.1      .1       0  445.76    .016       0
  475.57      .1       0   535.2     .12       0
Bank Sta=403.1,418.1
XS Rating Curve= 0 ,0
Exp/Cntr=0.3,0.1

Type RM Length L Ch R = 1 ,10123.5 ,197.2,198.8,200.4
XS GIS Cut Line= 3
     1761651.459      335669.534     1762060.956       335668.15
     1762470.454      335666.766
#Sta/Elev= 30
       0 1326.12       8 1321.01    19.9 1318.21   107.3 1253.89   202.8 1193.03
   242.5 1174.87  267.091159.132     330 1114.95   389.6 1063.06     402 1055.55
   413.5 1054.52     417 1054.78   444.31061.833     493 1061.82  503.381066.773
   516.8 1073.36   556.6 1073.41   564.6 1080.46   576.5 1099.66  591.99 1110.85
   604.3 1115.53   636.1 1136.63     648 1138.21     664 1150.28   691.8 1154.32
   711.7 1161.02   731.5 1170.62   743.5 1173.53   787.2  1195.5     819 1206.61
#Mann= 7 ,-1 , 0
       0      .1       0  267.09     .12       0     402    .045       0
     417     .12       0   444.3    .016       0  503.38      .1       0
  591.99     .12       0
Bank Sta=402,417
XS Rating Curve= 0 ,0
Exp/Cntr=0.3,0.1

Type RM Length L Ch R = 1 ,9924.7  ,289.4,301.2,313.8
XS GIS Cut Line= 2
       1761645.5      335839.452     1762433.695      335891.536
#Sta/Elev= 30
       0 1330.73    31.9 1307.77    47.9 1305.02    67.8 1292.98   175.5 1215.35
  193.851205.182   215.4 1188.34   227.4 1183.95   251.3 1168.65   344.1  1100.2
     395  1056.9   408.9 1050.54   418.9 1049.57   423.9 1050.26  430.621052.264
  460.221057.336   522.6 1056.82   534.6 1054.35  549.01 1061.89   610.4 1107.24
   642.3 1107.68   646.3 1112.88   654.3 1130.43   658.3 1134.52   666.2 1140.71
   678.2 1145.78   702.2 1165.18     754 1190.09     774 1195.58   789.9 1205.59
#Mann= 8 ,-1 , 0
       0      .1       0  193.85     .12       0   344.1     .12       0
   408.9    .045       0   423.9     .12       0  430.62    .016       0
  460.22      .1       0  549.01     .12       0
#XS Ineff= 2 , 0
                          474.94         1058.67
Permanent Ineff=
       F       F
Bank Sta=408.9,423.9
XS Rating Curve= 0 ,0
Exp/Cntr=0.3,0.1

Type RM Length L Ch R = 1 ,9623.5  ,393.6,392,389.2
XS GIS Cut Line= 3
     1761623.203      335915.915     1761967.902      336143.877
     1762299.565      336382.932
#Sta/Elev= 30
       0 1312.03    11.9 1303.67    31.8 1296.16    51.7 1281.11    63.6 1277.05
   131.1 1227.92   214.6 1176.36   222.5  1174.6   262.3 1148.65  283.291132.059
   365.6  1072.4   389.4 1049.11   405.8 1042.18   409.3 1041.59   420.8    1043
     441 1049.33  498.081045.542   524.4 1044.82   528.4 1046.05  534.491053.087
  549.381069.243   587.9 1101.13  607.311114.569   675.2 1160.98   683.2  1163.3
  716.541163.428   730.8 1177.44   754.6 1184.24   778.4 1203.13   822.1  1229.6
#Mann= 9 ,-1 , 0
       0      .1       0  283.29     .12       0   405.8    .045       0
   420.8     .12       0  498.08    .016       0  534.49      .1       0
  549.38     .12       0  607.31      .1       0  716.54     .12       0
#XS Ineff= 2 , 0
                          437.71         1050.61
Permanent Ineff=
       F       F
Bank Sta=405.8,420.8
XS Rating Curve= 0 ,0
Exp/Cntr=0.3,0.1

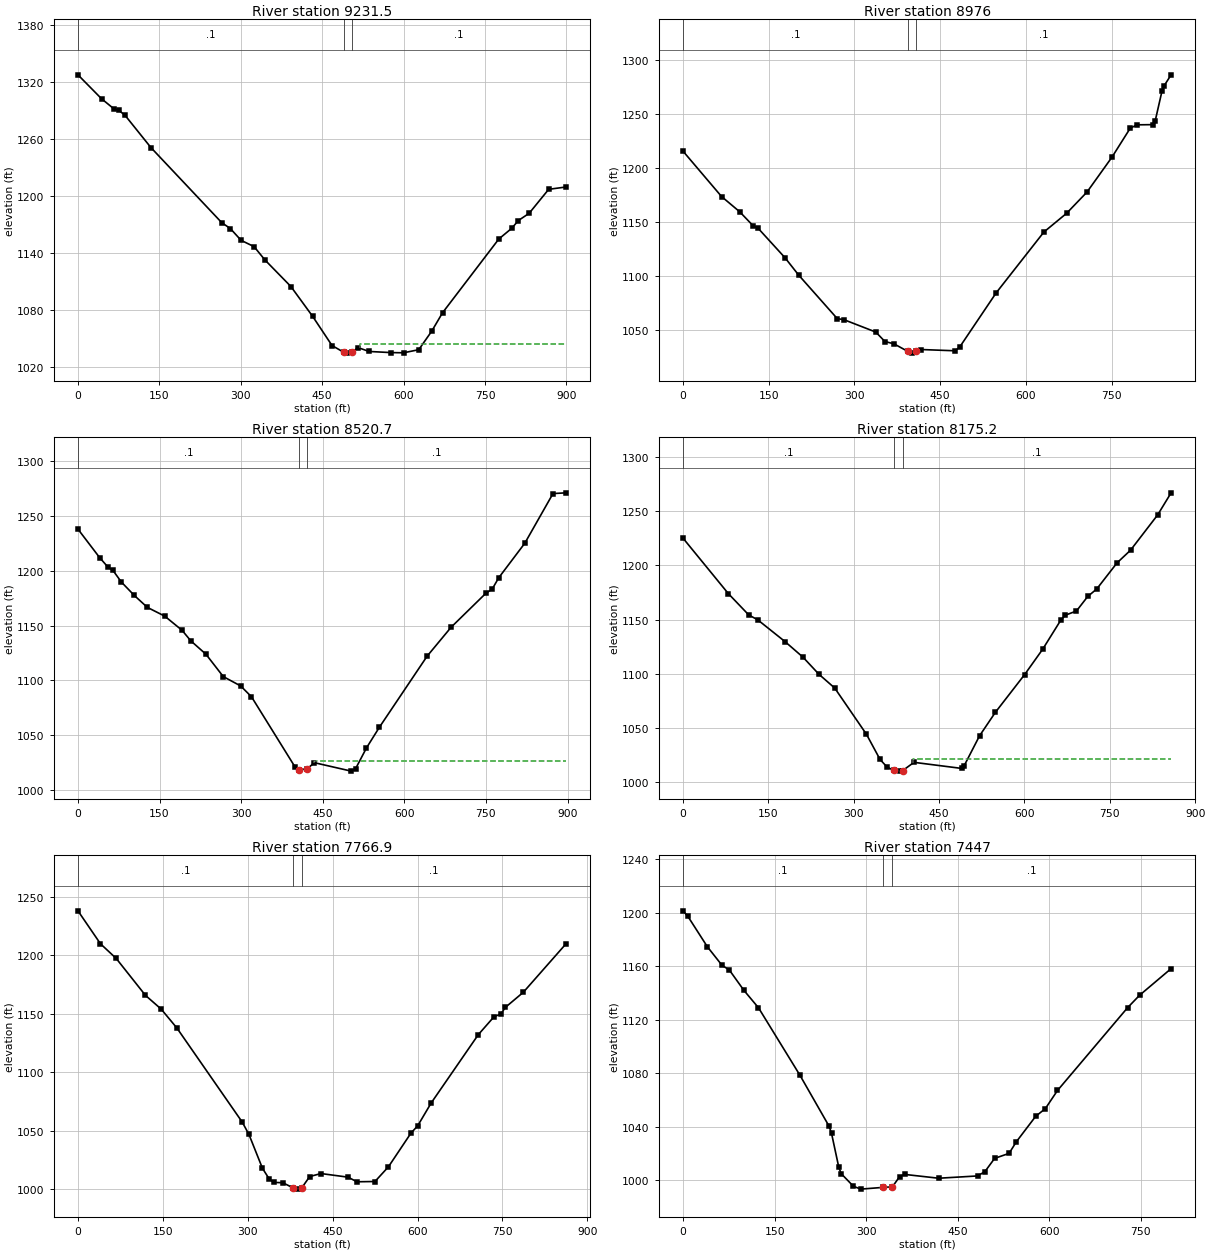
Type RM Length L Ch R = 1 ,9231.5  ,257.4,255.5,253.5
XS GIS Cut Line= 3
     1761461.924      336115.928     1761596.676        336380.1
     1762120.741      336677.415
#Sta/Elev= 30
       0 1327.58    43.5 1302.36    67.2 1291.31    75.1 1290.29      87 1284.76
   134.4 1250.97   264.9 1171.83   280.7 1165.63   300.6 1153.19   324.5 1146.54
   344.4 1132.58   392.3 1104.54   432.2 1073.23   468.1 1042.35   489.8  1035.2
   496.1 1034.35   504.8 1035.29     516 1040.23     536 1036.12   575.9 1034.93
   599.8 1034.71   627.8 1037.95   651.7 1057.44   671.6 1076.82   775.4 1154.63
   799.3 1165.95   811.3 1174.04   831.2 1181.66   867.2 1206.94   899.1  1209.4
#Mann= 3 , 0 , 0
       0      .1       0   489.8    .045       0   504.8      .1       0
#XS Ineff= 2 , 0
                           519.5         1043.75
Permanent Ineff=
       F       F
Bank Sta=489.8,504.8
XS Rating Curve= 0 ,0
Exp/Cntr=0.3,0.1

Type RM Length L Ch R = 1 ,8976    ,466.3,455.3,444.4
XS GIS Cut Line= 3
      1761283.02      336726.828     1761547.444      336656.055
      1762074.95      336897.729
#Sta/Elev= 30
       0 1215.39    67.4  1173.4    99.2 1159.25     123  1146.1   130.9 1144.26
   178.5 1116.64   202.3 1100.63   269.8 1060.32   281.7 1059.28   337.3 1047.84
   353.2  1039.1   369.1 1036.93   393.3 1029.94   400.9 1028.33   408.3 1029.96
   416.8 1031.66   476.4 1030.49   484.4 1034.21     548 1084.24   631.4  1140.5
   671.2 1157.89   706.9 1177.58   750.6 1209.91   782.4 1236.64   794.4 1239.82
   822.2    1240   826.1 1243.26   838.1 1271.19     842 1276.17     854 1286.14
#Mann= 3 , 0 , 0
       0      .1       0   393.3    .045       0   408.3      .1       0
Bank Sta=393.3,408.3
XS Rating Curve= 0 ,0
Exp/Cntr=0.3,0.1

Type RM Length L Ch R = 1 ,8520.7  ,350.6,345.6,340.3
XS GIS Cut Line= 2
     1761146.178      337145.562     1762042.373      337102.356
#Sta/Elev= 30
       0 1238.02    39.9 1212.02    55.8    1203    63.8 1200.75    79.8 1189.74
   103.7 1177.46   127.6 1166.62   159.5 1158.65   191.4 1145.72   207.4 1136.14
   235.3 1123.88   267.2 1103.48   299.1 1094.95     319 1085.09   398.8 1021.26
   406.4 1018.39   421.4  1019.4   434.7 1024.93   502.4 1017.24   510.4 1019.46
   530.4 1038.39   554.3 1057.38     642 1122.18   685.9 1148.44   749.7 1179.39
   761.6 1183.36   773.6 1193.68   821.5 1225.16   873.3 1270.44   897.2 1271.12
#Mann= 3 , 0 , 0
       0      .1       0   406.4    .045       0   421.4      .1       0
#XS Ineff= 2 , 0
                          434.71         1026.43
Permanent Ineff=
       F       F
Bank Sta=406.4,421.4
XS Rating Curve= 0 ,0
Exp/Cntr=0.3,0.1

Type RM Length L Ch R = 1 ,8175.2  ,420.3,408.3,396
XS GIS Cut Line= 3
     1761228.186      337568.587     1761676.084      337441.343
     1762016.628      337246.967
#Sta/Elev= 30
       0 1225.17    79.6 1173.96   115.4 1154.29   131.3 1149.72   179.1 1129.67
   210.9 1115.17   238.8 1099.46   266.6 1086.68   322.4 1043.91   346.2 1020.74
   358.2 1013.89   370.1 1010.56     382 1009.94     386 1010.46   405.9 1018.06
   489.4 1012.46   493.4 1014.28   521.1 1042.59   548.8 1064.21   600.3 1099.15
     632 1122.55   663.7 1149.32   671.6 1153.98   691.4 1157.91   711.2 1171.33
     727 1178.23   762.7 1202.36   786.4 1214.07     834 1246.64   857.7 1267.09
#Mann= 3 , 0 , 0
       0      .1       0   370.1    .045       0     386      .1       0
#XS Ineff= 2 , 0
                          404.75         1020.71
Permanent Ineff=
       F       F
Bank Sta=370.1,386
XS Rating Curve= 0 ,0
Exp/Cntr=0.3,0.1

Type RM Length L Ch R = 1 ,7766.9  ,320.3,319.9,319.3
XS GIS Cut Line= 3
     1761558.308      338057.599     1761935.421      337670.155
     1762090.937        337388.6
#Sta/Elev= 30
       0 1238.21    39.8 1209.98    67.6 1197.44   119.3 1165.82   147.1 1154.04
   174.9 1137.82   290.2 1057.35   302.1 1046.77     326 1017.74   337.9 1008.65
   345.9 1005.66   361.8 1005.39   380.6 1000.92   389.6  999.91   395.6 1001.12
   409.5 1010.69   429.4 1013.25   477.1 1010.16     493  1006.2   524.8 1006.44
   548.6 1019.04   588.3 1047.82   600.2 1054.08   624.1 1073.68   707.4 1132.21
   735.2 1147.56   747.2 1149.83   755.1  1155.5   786.9 1168.47   862.3 1209.96
#Mann= 3 , 0 , 0
       0      .1       0   380.6    .045       0   395.6      .1       0
Bank Sta=380.6,395.6
XS Rating Curve= 0 ,0
Exp/Cntr=0.3,0.1

Type RM Length L Ch R = 1 ,7447    ,299.9,303.4,307
XS GIS Cut Line= 3
     1761844.095      338211.534     1762191.317      337853.896
      1762212.15      337553.548
#Sta/Elev= 30
       0 1201.57       8 1197.37    39.9 1174.67    63.8 1160.85    75.8 1157.34
    99.7  1142.1   123.6 1129.06   191.4 1078.68   239.3 1040.43   243.2 1035.24
   255.2 1009.64   259.2 1004.94   279.1  995.58   291.1  993.44     327  994.72
   342.9  995.11   354.9 1002.88   362.9 1004.45   418.7 1001.59   482.5  1003.3
   494.5 1006.53   510.4 1016.44   534.1 1020.18     546 1028.86   577.7 1047.91
   593.5 1053.65   613.4 1067.22   728.2 1129.13     748 1138.48   799.5 1158.34
#Mann= 3 , 0 , 0
       0      .1       0     327    .045       0   342.9      .1       0
Bank Sta=327,342.9
XS Rating Curve= 0 ,0
Exp/Cntr=0.3,0.1

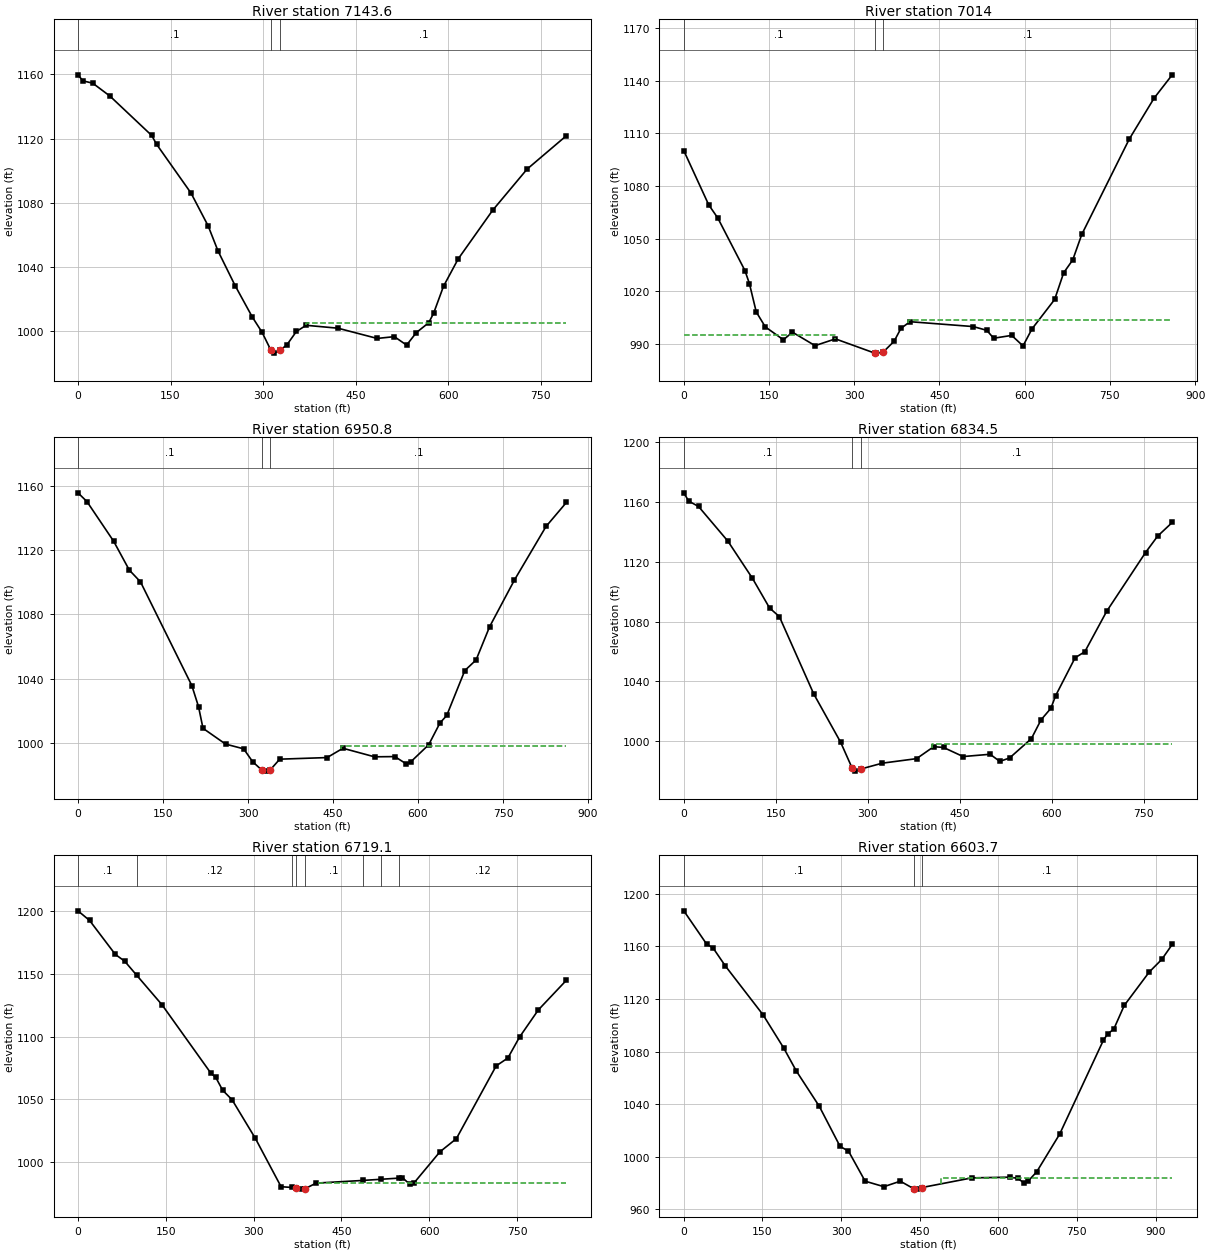
Type RM Length L Ch R = 1 ,7143.6  ,135.2,129.6,123.7
XS GIS Cut Line= 4
     1761942.185      338287.055      1762183.52      338259.588
     1762398.036      338102.644     1762589.755      337894.694
#Sta/Elev= 30
       0 1159.76       8    1156    23.9 1154.56    51.8 1146.52   119.5 1121.97
   127.4 1116.48   183.2 1086.08     211  1065.6     227 1049.97   254.8 1028.32
   282.6  1008.8   298.4  999.29  312.38  988.37   318.3  986.34  327.95   988.4
   338.1  991.24     354  999.84   369.8 1003.68   421.4 1001.87   484.9  995.49
   512.7  996.61   532.6  991.34   548.5  999.18   568.4 1005.26   576.4 1011.22
   592.4    1028   616.2 1045.06     672 1075.33   727.8 1100.98   791.5 1121.81
#Mann= 3 , 0 , 0
       0      .1       0  312.38    .045       0  327.95      .1       0
#XS Ineff= 2 , 0
                          369.93         1005.29
Permanent Ineff=
       F       F
Bank Sta=312.38,327.95
XS Rating Curve= 0 ,0
Exp/Cntr=0.3,0.1

Type RM Length L Ch R = 1 ,7014    ,63.8,63.2,62.6
XS GIS Cut Line= 3
     1762044.616      338342.611     1762206.074      338445.041
     1762638.505      337935.429
#Sta/Elev= 30
       0 1100.11    43.8 1069.24    59.8 1061.71   107.6 1031.73   115.5 1024.28
   127.5 1008.15   143.4  999.64   175.3  992.26   191.2  996.59     231  988.93
   266.8  992.79   335.8  984.69   338.4  984.66   350.8  985.22   370.2  991.45
   382.2  998.78   398.1 1002.58   509.5   999.8   533.3  997.65   545.3  993.15
   577.1  994.77     597  988.77   612.9  998.51   652.7 1015.26   668.6  1030.5
   684.5 1037.78   700.4 1052.32     784  1106.7   827.7 1130.04   859.6 1143.35
#Mann= 3 , 0 , 0
       0      .1       0   335.8    .045       0   350.8      .1       0
#XS Ineff= 2 , 0
          265.69  994.79  394.01         1003.57
Permanent Ineff=
       F       F
Bank Sta=335.8,350.8
XS Rating Curve= 0 ,0
Exp/Cntr=0.3,0.1

Type RM Length L Ch R = 1 ,6950.8  ,126.1,116.2,106.3
XS GIS Cut Line= 3
      1762364.06      338660.319     1762281.161      338455.892
     1762679.967      337953.954
#Sta/Elev= 30
       0 1155.74    15.8 1150.31      63 1125.55    90.6 1107.58   110.3 1100.26
   200.9 1035.62   212.7  1022.5   220.6 1008.98   260.4  999.15   292.3   996.2
   308.2  988.17   324.6  982.87   332.1   982.3   339.6  983.21     356  989.75
   439.6  990.75   467.5  996.55   523.2  991.22   559.1  991.36     579  986.85
   586.9  987.99   618.8  998.74   638.7 1012.32   650.6 1016.97   682.5 1044.97
   702.4 1051.58   726.3 1072.32   770.1 1101.41   825.8 1134.76   861.7 1149.72
#Mann= 3 , 0 , 0
       0      .1       0   324.6    .045       0   339.6      .1       0
#XS Ineff= 2 , 0
                          464.67          998.21
Permanent Ineff=
       F       F
Bank Sta=324.6,339.6
XS Rating Curve= 0 ,0
Exp/Cntr=0.3,0.1

Type RM Length L Ch R = 1 ,6834.5  ,115.7,115.5,115.1
XS GIS Cut Line= 3
     1762391.838      338686.361     1762509.041      338200.908
      1762699.13      337972.819
#Sta/Elev= 30
       0 1166.24       8  1160.7      24  1157.1    71.9 1133.86   111.9 1108.98
   139.8 1089.12   155.8 1083.31   211.8 1031.56   255.7  999.17   274.2  982.09
   279.7  979.82   289.2   981.3   323.6  985.15   379.5  988.18   407.5  996.21
   423.5  995.66   455.4  989.58   499.4  991.12   515.2  986.34   531.1  988.62
   566.7 1001.58   582.5 1014.22   598.4 1021.85   606.3 1030.41     638 1055.78
   653.8 1059.78   689.4 1086.84   752.8 1126.24   772.6 1137.26   796.3 1146.39
#Mann= 3 , 0 , 0
       0      .1       0   274.2    .045       0   289.2      .1       0
#XS Ineff= 2 , 0
                           404.3          997.92
Permanent Ineff=
       F       F
Bank Sta=274.2,289.2
XS Rating Curve= 0 ,0
Exp/Cntr=0.3,0.1

Type RM Length L Ch R = 1 ,6719.1  ,141.3,115.4,86.3
XS GIS Cut Line= 3
     1762486.949      338795.109     1762608.043      338266.463
     1762747.366      338009.953
#Sta/Elev= 30
       0  1200.5    19.9 1192.78    63.8 1165.67    79.8 1160.26  100.551148.891
   143.6  1125.4   227.3 1070.61   235.3 1067.46   247.2 1057.11   263.2 1049.56
   303.1 1018.61   346.9  980.09  365.69979.4682   372.1  978.68   382.8  978.15
   387.1  978.31   406.8  982.95   486.9 985.107   517.2 986.013  548.07986.9439
   554.3  987.28   566.3   982.2   574.3  983.28   618.3 1007.98   646.3 1018.45
   714.3 1076.61   734.3 1082.92   754.3 1099.68   786.3 1121.32   834.2 1145.01
#Mann= 8 ,-1 , 0
       0      .1       0  100.55     .12       0  365.69      .1       0
   372.1    .045       0   387.1      .1       0   486.9    .016       0
   517.2      .1       0  548.07     .12       0
#XS Ineff= 2 , 0
                           409.8          983.42
Permanent Ineff=
       F       F
Bank Sta=372.1,387.1
XS Rating Curve= 0 ,0
Exp/Cntr=0.3,0.1

Type RM Length L Ch R = 1 ,6603.7  ,49.3,51.5,55.4
XS GIS Cut Line= 4
     1762575.881      338816.793      1762737.34      338466.533
     1762626.532      338374.276     1762830.699      338028.182
#Sta/Elev= 30
       0  1186.9    43.7 1161.54    55.7 1158.75    79.5 1144.89   151.1 1107.93
   190.8 1082.54   214.7 1065.17   258.4 1038.43   298.2 1007.86   314.1 1004.41
   345.9  981.51   381.7  977.33     413  981.51  438.48  975.81   444.1  975.47
  453.74  976.64   549.8  984.03   621.4  984.55   637.3  983.66   649.2     980
   657.2  981.72   673.1  988.56   716.9 1017.19   800.4 1088.57   808.4 1093.23
   820.3  1097.1   840.2    1115   887.9 1140.42   911.8 1149.99   931.7 1161.35
#Mann= 3 , 0 , 0
       0      .1       0  438.48    .045       0  453.74      .1       0
#XS Ineff= 2 , 0
                          491.24          983.63
Permanent Ineff=
       F       F
Bank Sta=438.48,453.74
XS Rating Curve= 0 ,0
Exp/Cntr=0.3,0.1

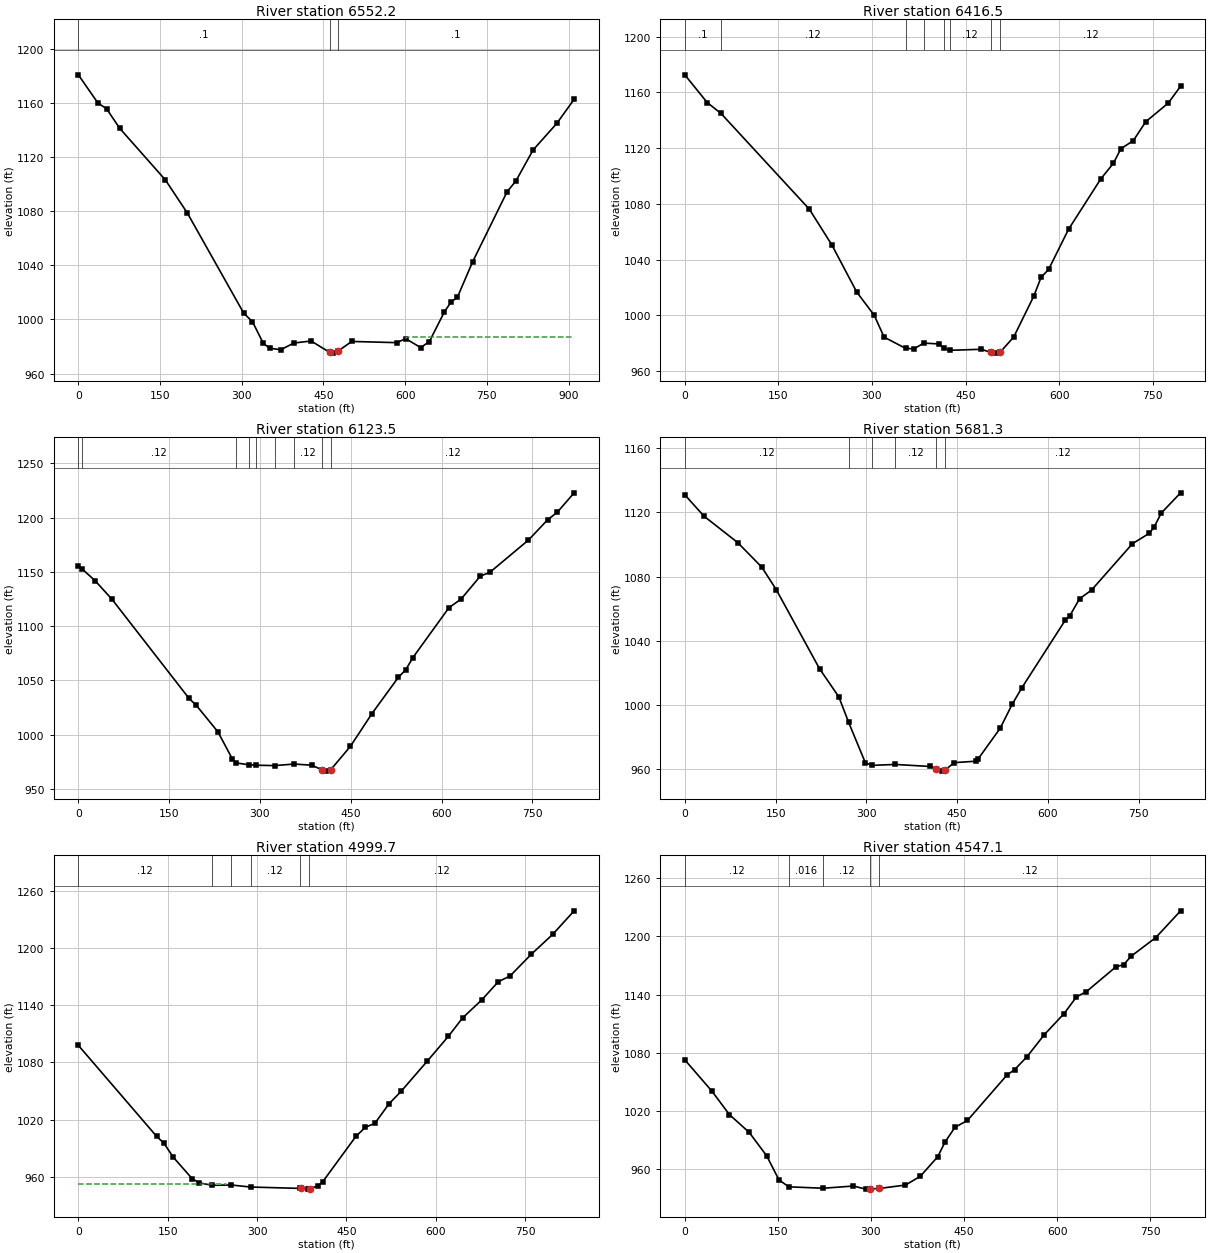
Type RM Length L Ch R = 1 ,6552.2  ,107.1,135.7,165.2
XS GIS Cut Line= 4
     1762597.626      338822.453     1762771.194      338440.491
     1762673.537      338349.345     1762864.553      338047.713
#Sta/Elev= 30
       0 1180.84      36 1159.98    51.9 1155.74    75.9 1141.32   159.8 1103.12
   199.8 1078.88   303.7 1004.57   319.7  998.32   339.6  982.25   351.6   978.7
   371.6  977.58   395.6  982.54   427.4  984.05   461.7  975.55   466.7  975.08
   476.7  976.58     502  983.72   584.9  982.82   600.7  985.82   628.5  979.18
   644.4  983.63   672.1 1005.65     684 1012.73   695.9 1016.43   723.7  1042.5
   787.2 1094.48     803 1102.23   834.8 1125.26   878.4 1144.96   910.2 1162.78
#Mann= 3 , 0 , 0
       0      .1       0   461.7    .045       0   476.7      .1       0
#XS Ineff= 2 , 0
                          601.47           987.2
Permanent Ineff=
       F       F
Bank Sta=461.7,476.7
XS Rating Curve= 0 ,0
Exp/Cntr=0.3,0.1

Type RM Length L Ch R = 1 ,6416.5  ,294.1,293,291.9
XS GIS Cut Line= 2
     1762657.522       338845.89     1762988.251      338123.234
#Sta/Elev= 30
       0 1172.57    35.9  1152.7   58.081144.818   199.7  1076.1   235.6 1050.58
   275.6 1016.66   303.5 1000.08   319.5  984.33   353.8 976.286   367.4  975.93
  382.91980.0457   407.4  979.45  415.39 976.327  424.76974.8789   475.2  975.61
   490.6  973.34   499.2  972.85   505.6  973.58   527.2  984.43   559.1 1013.49
   571.1 1027.29   583.1 1032.91     615 1061.68   666.9 1097.99   686.9 1109.03
   698.9 1119.52   718.9 1125.35   738.8 1138.91   774.8 1152.25   794.7 1164.42
#Mann= 8 ,-1 , 0
       0      .1       0   58.08     .12       0   353.8      .1       0
  382.91    .016       0  415.39      .1       0  424.76     .12       0
   490.6    .045       0   505.6     .12       0
Bank Sta=490.6,505.6
XS Rating Curve= 0 ,0
Exp/Cntr=0.3,0.1

Type RM Length L Ch R = 1 ,6123.5  ,435,442.2,449.3
XS GIS Cut Line= 3
     1762966.097       338917.16      1763118.18      338536.949
     1763270.264      338156.737
#Sta/Elev= 30
       0 1155.91    6.411152.657    27.8 1141.84    55.7 1124.69   182.9 1033.33
   194.8 1027.03   230.6 1002.51   254.4  977.58  260.91973.8815  281.34 972.184
  292.72971.7911  324.53 971.408  356.34 972.866   385.6  971.77     402  967.64
   409.5  966.32     417  967.66   449.3  989.09     485 1019.37   528.8 1052.95
   540.7 1059.65   552.6    1071   612.3 1117.11   632.1 1124.88     664 1146.13
   679.8 1149.64   743.5 1179.38   775.3 1198.14   791.2 1205.06     819 1222.94
#Mann= 9 ,-1 , 0
       0      .1       0    6.41     .12       0  260.91      .1       0
  281.34     .12       0  292.72      .1       0  324.53    .016       0
  356.34     .12       0     402    .045       0     417     .12       0
Bank Sta=402,417
XS Rating Curve= 0 ,0
Exp/Cntr=0.3,0.1

Type RM Length L Ch R = 1 ,5681.3  ,670.9,681.6,691.7
XS GIS Cut Line= 3
     1763237.822      339059.828     1763500.438      338745.626
     1763763.053      338431.423
#Sta/Elev= 30
       0 1130.94    31.8 1117.65    87.5 1101.18   127.2  1085.9   151.1 1071.89
   222.6 1022.62   254.4 1005.16  270.71989.1732   298.2  964.13  309.21962.4711
   347.7963.0365   405.5  961.78   415.3  960.02   425.4  958.88   430.3  959.72
   445.3  964.17   481.1  965.06     485  966.73   520.8  985.48   540.7 1000.45
   556.6  1010.7   628.2 1052.73   636.1 1055.73     652 1066.19   671.9 1071.66
   739.5 1100.55   767.3 1106.99   775.3 1110.97   787.2 1119.69     819  1132.2
#Mann= 6 ,-1 , 0
       0     .12       0  270.71      .1       0  309.21    .016       0
   347.7     .12       0   415.3    .045       0   430.3     .12       0
Bank Sta=415.3,430.3
XS Rating Curve= 0 ,0
Exp/Cntr=0.3,0.1

Type RM Length L Ch R = 1 ,4999.7  ,453.3,452.5,451.9
XS GIS Cut Line= 2
     1763544.197      339385.986      1764306.35      339050.916
#Sta/Elev= 30
       0 1097.97   131.5 1002.25   143.4  995.36   159.3  980.47   191.2  957.75
   203.2  953.32  224.75950.8445  257.01951.1463  289.27949.0085   371.8  947.59
   374.4  947.48   386.4  946.81   386.8  946.91  388.58  947.35   402.3  950.17
   410.3   954.5   466.1 1002.24     482 1011.86   497.9 1015.94   521.8 1036.57
   541.8 1049.45   585.6 1081.13   621.4 1107.45   645.3 1126.82   677.2 1145.55
   705.1 1164.76     725 1170.91   760.8 1193.82   796.7 1214.69   832.6 1239.36
#Mann= 6 ,-1 , 0
       0     .12       0  224.75    .016       0  257.01      .1       0
  289.27     .12       0   371.8    .045       0   386.8     .12       0
#XS Ineff= 2 , 0
          247.45  952.31
Permanent Ineff=
       F       F
Bank Sta=374.4,388.58
XS Rating Curve= 0 ,0
Exp/Cntr=0.3,0.1

Type RM Length L Ch R = 1 ,4547.1  ,510.6,507.9,506.2
XS GIS Cut Line= 2
     1763785.517      339752.305     1764504.267      339403.347
#Sta/Elev= 30
       0 1072.63    43.9 1040.18    71.9 1016.17   103.9   997.7   131.8  973.79
   151.8  948.78  167.61941.6638  223.13940.2014   271.6  942.49   291.6  939.29
   298.1   939.5   313.1  939.96   355.6  943.48   379.5  952.53   407.5  972.62
   419.5  988.04   435.4 1003.06   455.4 1010.07   519.3 1057.05   531.3 1062.41
   551.3 1075.74   579.3 1098.56   611.2 1120.33   631.2 1137.58   647.2 1142.99
   695.1 1168.76   707.1 1170.67   719.1 1179.44     759 1198.73     799 1226.31
#Mann= 5 ,-1 , 0
       0     .12       0  167.61    .016       0  223.13     .12       0
   298.1    .045       0   313.1     .12       0
Bank Sta=298.1,313.1
XS Rating Curve= 0 ,0
Exp/Cntr=0.3,0.1