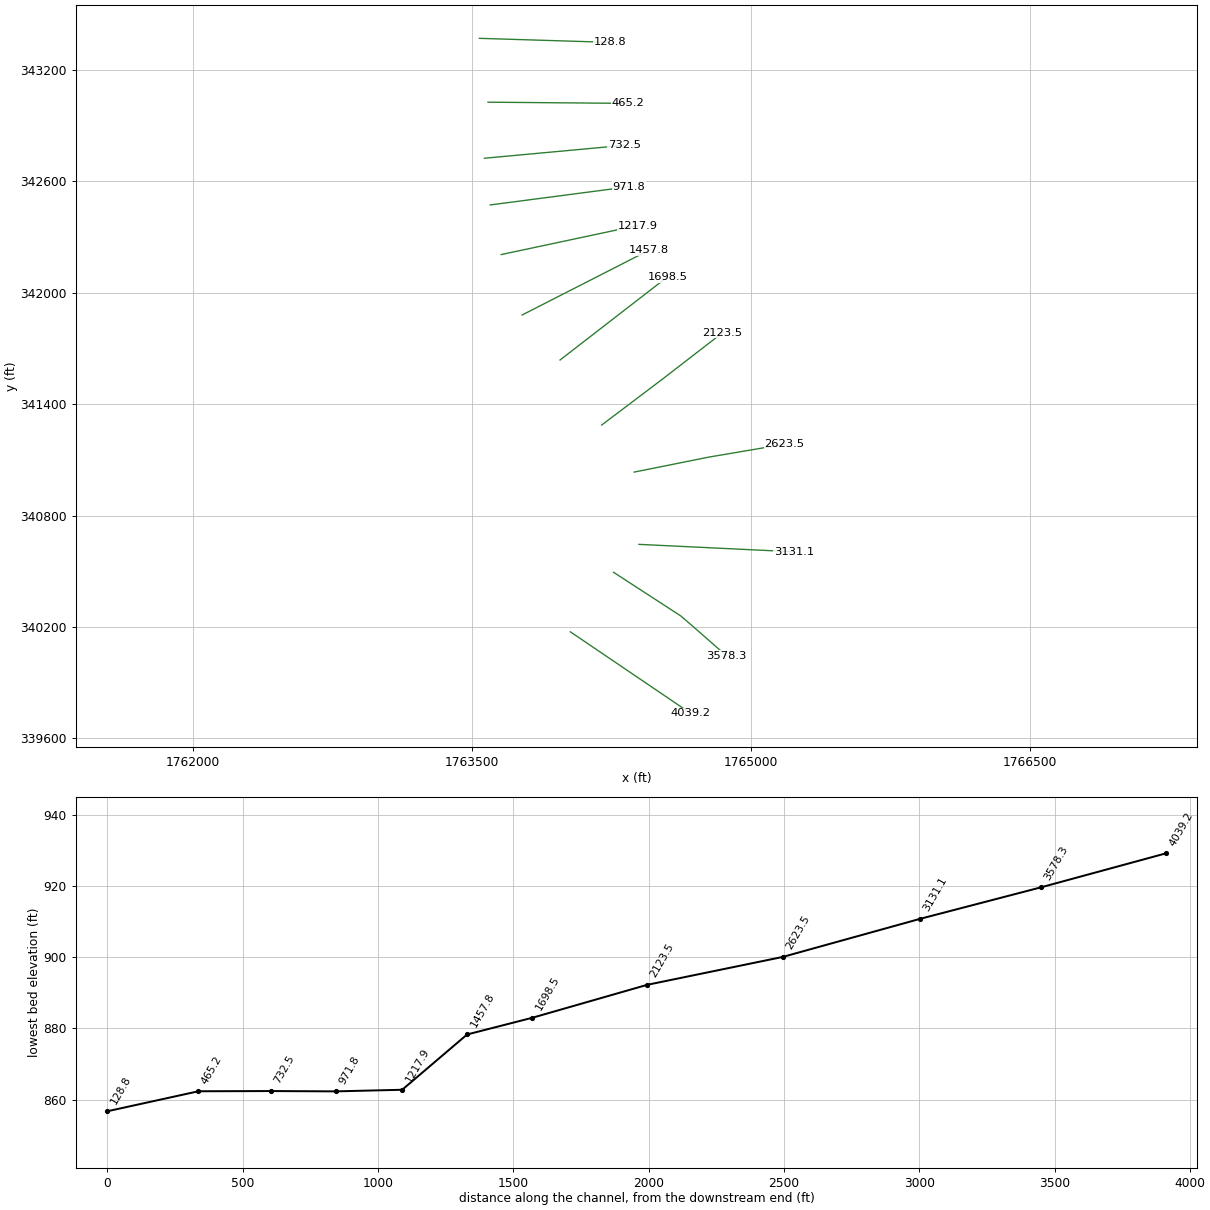
HEC-RAS study CASEYCK.prj: CASEYCK

--- CASEYCK.g01 (geometry) --- (continued)

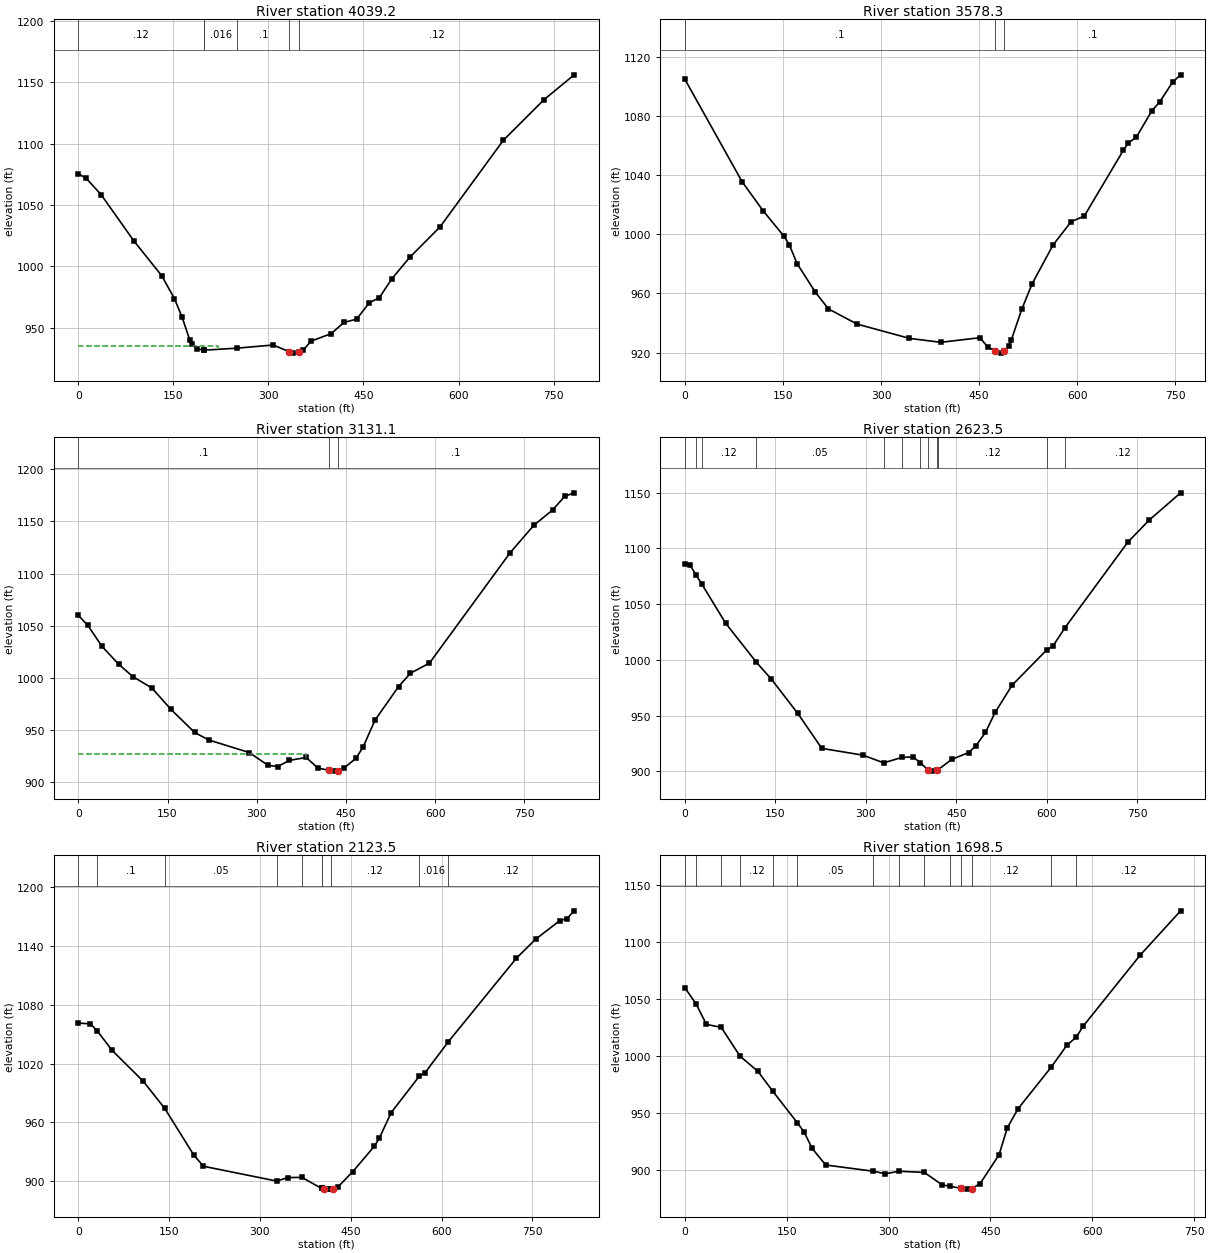
Type RM Length L Ch R = 1 ,4039.2  ,462.7,460.9,458.9
XS GIS Cut Line= 2
     1764028.572       340174.18     1764676.142      339734.944
#Sta/Elev= 30
       0 1075.28      12  1071.8    35.9 1058.37    87.8 1020.49   131.7  992.18
   151.7  973.51   163.7  958.58   175.7  940.08   179.6  936.25   187.6  932.67
  197.96931.5628   198.7 931.548  250.58   933.2   307.4  935.75   333.1  930.28
   339.3  929.14   348.1  929.77   355.3  931.82   367.3  938.89   399.2  945.09
   419.2  954.16   439.2  956.85   459.1  970.14   475.1  974.36     495  989.88
     523  1007.2   570.9 1032.07   670.7 1102.61   734.6 1135.57   782.5 1155.98
#Mann= 6 ,-1 , 0
       0     .12       0  197.96      .1       0   198.7    .016       0
  250.58      .1       0   333.1    .045       0   348.1     .12       0
#XS Ineff= 2 , 0
          219.64  935.09
Permanent Ineff=
       F       F
Bank Sta=333.1,348.1
XS Rating Curve= 0 ,0
Exp/Cntr=0.3,0.1

Type RM Length L Ch R = 1 ,3578.3  ,432.3,447.3,462.1
XS GIS Cut Line= 4
     1764261.211      340494.493     1764622.756      340259.501
     1764698.277      340194.397      1764868.85      340044.658
#Sta/Elev= 30
       0 1104.75    87.8  1035.3   119.8 1015.77   151.7  998.55   159.7  992.81
   171.7  980.06   199.6  960.77   219.6  949.48   263.5  939.21   343.4  929.58
   391.3  926.92   451.1  930.02   463.1  923.76   473.5  921.27     483  919.61
   488.5  920.73     495  924.35     499  928.35     515  949.18   530.9  966.45
   562.8  992.61   590.6 1008.48   610.6  1012.2   670.3 1056.66   678.2 1061.72
   690.2 1065.51   714.1 1083.53     726  1089.4   745.9 1102.89   757.9 1107.68
#Mann= 3 , 0 , 0
       0      .1       0   473.5    .045       0   488.5      .1       0
Bank Sta=473.5,488.5
XS Rating Curve= 0 ,0
Exp/Cntr=0.3,0.1

Type RM Length L Ch R = 1 ,3131.1  ,501.8,507.6,512.7
XS GIS Cut Line= 2
     1764397.496      340644.918     1765230.279       340604.98
#Sta/Elev= 30
       0 1059.92      16 1050.28    39.9 1030.14    67.8 1013.13    91.8  1001.2
   123.7  990.36   155.6  969.96   195.5  947.78   219.4  940.58   287.2  928.58
   319.1  916.26   335.1  915.17     355  921.05     383  923.81   402.9  913.74
   420.8  911.61   430.8  910.75   435.8  911.04   446.8  913.66   466.7     923
   478.7  933.64   498.6  959.33   538.5  991.78   558.5 1004.52   590.4 1014.19
     726 1119.87   765.9 1146.15   797.8    1161   817.8 1173.89   833.7 1177.26
#Mann= 3 , 0 , 0
       0      .1       0   420.8    .045       0   435.8      .1       0
#XS Ineff= 2 , 0
           382.7  926.79
Permanent Ineff=
       F       F
Bank Sta=420.8,435.8
XS Rating Curve= 0 ,0
Exp/Cntr=0.3,0.1

Type RM Length L Ch R = 1 ,2623.5  ,489.4,500,511.2
XS GIS Cut Line= 3
     1764372.003       341034.05     1764774.224      341114.849
     1765179.659      341183.697
#Sta/Elev= 30
       0 1086.37       8 1085.55   18.721076.097   28.361067.897    67.7 1032.85
  118.74997.7211   143.4  982.68   187.2  951.86     227  920.48   294.8  914.43
  329.62907.4843  359.75912.3694   378.4  912.81  389.87907.6356   402.8   901.3
   410.3  900.05   417.8  900.83  419.95901.4719   442.2  910.56   470.2   916.7
   482.1  922.68   498.1  934.76   514.1  952.71     542  977.04   599.71008.927
   609.9 1012.26  629.661028.657   733.7 1105.47   769.6 1125.57   821.5 1149.97
#Mann= 12 ,-1 , 0
       0    .016       0   18.72      .1       0   28.36     .12       0
  118.74     .05       0  329.62      .1       0  359.75    .016       0
  389.87      .1       0   402.8    .045       0   417.8      .1       0
  419.95     .12       0   599.7    .016       0  629.66     .12       0
Bank Sta=402.8,417.8
XS Rating Curve= 0 ,0
Exp/Cntr=0.3,0.1

Type RM Length L Ch R = 1 ,2123.5  ,424.5,425,425.2
XS GIS Cut Line= 3
     1764197.394      341287.584     1764524.075      341534.496
     1764848.008      341785.061
#Sta/Elev= 30
       0 1061.12    19.9 1060.37    31.61052.874    55.7 1033.43   107.3  1001.9
  142.67974.3545   190.8  926.79   206.7  915.48  327.79900.4113   345.9  903.99
  369.38904.1597  401.84892.9356     402  892.91   405.5  892.36   413.5  892.23
     417  892.25   421.4  892.31   429.4  894.82   453.2  909.94     489   935.9
     497  943.83   516.8  970.12  563.051006.914   572.5 1010.49  611.321042.258
   723.6 1127.14   755.4 1146.44   795.2 1165.28   807.1 1167.37     819  1175.3
#Mann= 10 ,-1 , 0
       0    .016       0    31.6      .1       0  142.67     .05       0
  327.79    .016       0  369.38      .1       0  401.84     .12       0
     402    .045       0     417     .12       0  563.05    .016       0
  611.32     .12       0
Bank Sta=405.5,421.4
XS Rating Curve= 0 ,0
Exp/Cntr=0.3,0.1

Type RM Length L Ch R = 1 ,1698.5  ,245.1,240.7,236.2
XS GIS Cut Line= 2
     1763973.422      341637.707     1764550.679      342084.756
#Sta/Elev= 30
       0 1059.94   16.321045.921    31.9 1027.68   53.681025.044   81.39999.7308
   107.7  986.39  129.63968.8849  165.76 941.216   175.6  933.24   187.5  918.75
   207.5  904.16  277.83898.6852   295.2  896.44  315.19898.6588  352.55897.6875
     379  886.73  389.91885.5137   407.2  883.61   414.9  882.97   422.2  883.26
   434.9  887.84   462.8  913.18   474.8  936.69   490.7  953.56  539.34989.9802
   562.6 1009.32   576.7 1016.68   586.5 1026.01   670.3 1088.33   730.1 1127.43
#Mann= 14 ,-1 , 0
       0     .12       0   16.32    .016       0   53.68      .1       0
   81.39     .12       0  129.63      .1       0  165.76     .05       0
  277.83     .04       0  315.19    .016       0  352.55      .1       0
  389.91     .12       0   407.2    .045       0   422.2     .12       0
  539.34    .016       0   576.7     .12       0
Bank Sta=407.2,422.2
XS Rating Curve= 0 ,0
Exp/Cntr=0.3,0.1

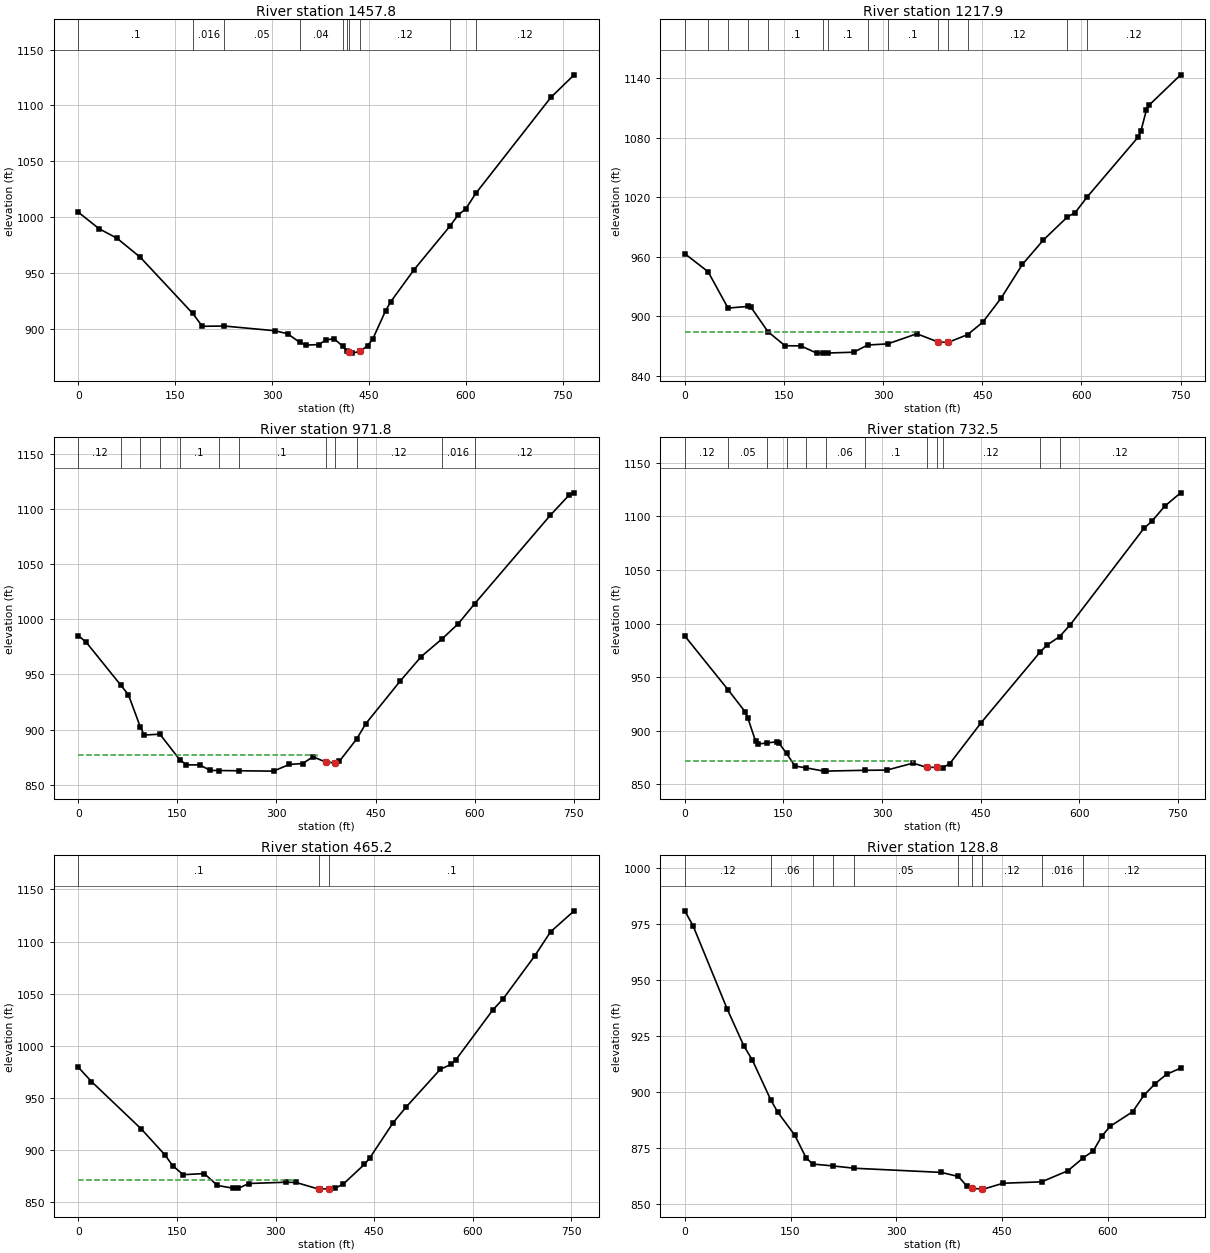
Type RM Length L Ch R = 1 ,1457.8  ,246,239.9,233.9
XS GIS Cut Line= 2
     1763769.544      341879.996     1764453.138      342229.389
#Sta/Elev= 30
       0 1004.38      32  989.67      60  981.03      96  964.02  177.13913.7814
   191.9  902.32  226.12902.5168   303.9  898.33   323.9  895.67  342.98887.8224
   351.9  885.46   371.9  885.91   383.8  890.08   395.8  891.26  409.33884.4517
   416.2  880.33   419.8  878.95   423.8  878.28   435.8   879.8   447.8   884.8
   455.8  890.83   475.8  916.32   483.8  924.35   519.8  952.94  575.18991.7873
   587.8 1001.74   599.8 1007.34  615.481021.318   731.7 1107.18   767.7 1127.34
#Mann= 10 ,-1 , 0
       0      .1       0  177.13    .016       0  226.12     .05       0
  342.98     .04       0  409.33      .1       0   416.2    .045       0
   419.8    .045       0   435.8     .12       0  575.18    .016       0
  615.48     .12       0
Bank Sta=419.8,435.8
XS Rating Curve= 0 ,0
Exp/Cntr=0.3,0.1

Type RM Length L Ch R = 1 ,1217.9  ,247.7,246.1,244.3
XS GIS Cut Line= 2
     1763656.582      342205.199     1764390.088      342361.449
#Sta/Elev= 30
       0  963.02   35.18944.8818   65.38908.1677   95.58909.8477    99.7  909.41
  125.78  884.37   151.6  870.19   175.5  870.08   199.5  862.75  208.96862.8056
  216.37862.8773   255.3  863.66  276.77870.9214  306.97872.0865     351  882.27
   383.7  873.83   398.7   873.7  427.77881.4037   450.8  893.98   478.7  918.43
   510.6  952.17   542.5  976.88  578.761000.106   590.4 1004.36  608.961020.474
   686.1 1080.89   690.1  1087.1   698.1 1107.52   702.1 1112.65     750 1143.37
#Mann= 14 ,-1 , 0
       0     .12       0   35.18     .05       0   65.38    .016       0
   95.58     .05       0  125.78      .1       0  208.96     .06       0
  216.37      .1       0  276.77     .05       0  306.97      .1       0
   383.7    .045       0   398.7      .1       0  427.77     .12       0
  578.76    .016       0  608.96     .12       0
#XS Ineff= 2 , 0
          353.35  884.46
Permanent Ineff=
       F       F
Bank Sta=383.7,398.7
XS Rating Curve= 0 ,0
Exp/Cntr=0.3,0.1

Type RM Length L Ch R = 1 ,971.8   ,240.2,239.4,238.5
XS GIS Cut Line= 2
     1763598.104      342472.444     1764342.461        342570.1
#Sta/Elev= 30
       0   985.2      12  979.09    63.9  940.56    75.9  931.42   93.69902.5502
    99.8  895.02  123.48895.8172  153.27872.8359   163.7  867.97   183.7  867.94
   199.7  862.98  212.85862.8306  242.64862.6272   295.5   862.3   319.5   868.4
   339.4  869.14   355.4  875.32   374.3  870.55   389.3  869.77   395.3   871.3
  421.38 891.414   435.3  905.38   487.2  943.89   519.1  966.15  550.72982.2243
     575  995.82  600.111014.143   714.8 1094.44   742.8 1112.46   750.7 1114.66
#Mann= 12 ,-1 , 0
       0     .12       0    63.9     .05       0   93.69    .016       0
  123.48     .05       0  153.27      .1       0  212.85     .06       0
  242.64      .1       0   374.3    .045       0   389.3      .1       0
  421.38     .12       0  550.72    .016       0  600.11     .12       0
#XS Ineff= 2 , 0
          360.78  876.86
Permanent Ineff=
       F       F
Bank Sta=374.3,389.3
XS Rating Curve= 0 ,0
Exp/Cntr=0.3,0.1

Type RM Length L Ch R = 1 ,732.5   ,269.5,267.3,264.9
XS GIS Cut Line= 2
     1763566.521      342723.862     1764317.389      342793.306
#Sta/Elev= 30
       0  988.44    65.7938.3468    91.8   917.7    95.8  912.09   107.7   890.2
   111.7  887.68  125.02888.7037   139.6   889.7   143.6  888.21  154.68878.9505
   167.6  867.12  184.35865.4645   211.5  862.39  214.01862.4158  273.33863.1654
   307.2  863.34   347.1  869.86   368.3  865.84   383.3     866  391.98865.5374
     403  869.38   450.8  907.62  540.29973.3414   550.6  979.82  569.95  987.82
   586.5  999.06   698.2 1088.77   710.2 1095.32   730.1 1109.57   754.1 1121.93
#Mann= 12 ,-1 , 0
       0     .12       0    65.7     .05       0  125.02    .016       0
  154.68      .1       0  184.35    .016       0  214.01     .06       0
  273.33      .1       0   368.3    .045       0   383.3      .1       0
  391.98     .12       0  540.29    .016       0  569.95     .12       0
#XS Ineff= 2 , 0
          346.75   872.3
Permanent Ineff=
       F       F
Bank Sta=368.3,383.3
XS Rating Curve= 0 ,0
Exp/Cntr=0.3,0.1

Type RM Length L Ch R = 1 ,465.2   ,337.1,336.4,336.1
XS GIS Cut Line= 2
     1763585.766      343025.692     1764339.811      343019.254
#Sta/Elev= 30
       0   979.3      20  965.58    95.8  920.04   131.7  895.16   143.6  884.72
   159.6   876.2   191.5  877.27   211.5  865.87   235.4   863.2   243.4   863.1
   259.3  867.73   315.2  868.95   331.2  868.72   365.5  862.37   367.1  862.33
   380.5  862.84     391  863.41     403  867.22   434.9  885.99   442.9  891.89
   478.8  926.13   498.7  941.22   550.6  977.41   566.6  981.96   574.5  986.74
   630.4 1034.31   646.4 1045.24   694.2 1086.24   718.2 1109.32   754.1 1129.47
#Mann= 3 , 0 , 0
       0      .1       0   365.5    .045       0   380.5      .1       0
#XS Ineff= 2 , 0
          330.13  870.71
Permanent Ineff=
       F       F
Bank Sta=365.5,380.5
XS Rating Curve= 0 ,0
Exp/Cntr=0.3,0.1

Type RM Length L Ch R = 1 ,128.8   ,120.9,128.8,136.3
XS GIS Cut Line= 2
     1763539.394      343369.478     1764242.519      343347.777
#Sta/Elev= 30
       0  980.81      12  973.95      60  937.14    83.9  920.51    95.9  914.25
  122.17896.3791   131.9  891.01   155.9  880.85   171.9  870.78  181.27867.9111
  210.82867.0424  240.37866.0358   363.7  864.18  388.12862.3581   399.7  858.26
   406.8     857   421.8  856.81   423.7  856.72   451.6  859.35  506.32859.9644
   543.6  864.93  565.42870.6795   579.6  873.77   591.6  880.32   603.5  884.72
   635.5  891.24   651.5  898.58   667.5   903.8   683.5  907.91   703.5  910.68
#Mann= 10 ,-1 , 0
       0     .12       0  122.17     .06       0  181.27     .06       0
  210.82    .016       0  240.37     .05       0  388.12     .12       0
   406.8    .045       0   421.8     .12       0  506.32    .016       0
  565.42     .12       0
Bank Sta=406.8,421.8
XS Rating Curve= 0 ,0
Exp/Cntr=0.3,0.1
LCMann Table=0

Chan Stop Cuts=-1
Use User Specified Reach Order=0
Composite Channel Slope=5